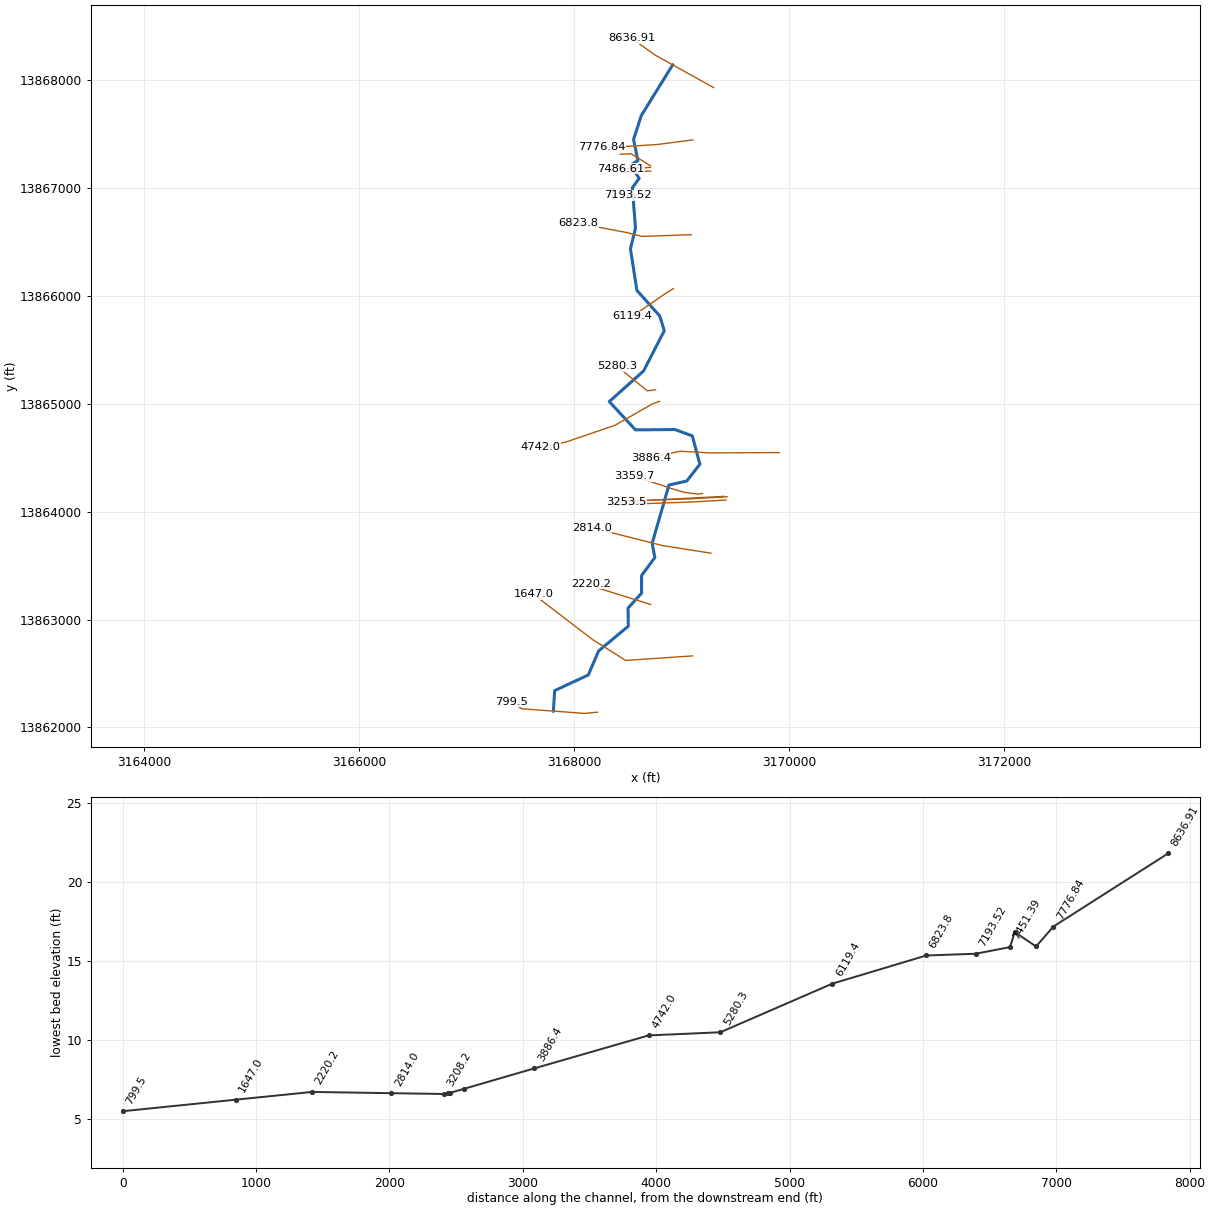
--- P110-00-00.prj (project) ---

Proj Title=P110-00-00
Current Plan=p01
Default Exp/Contr=.3,.1
English Units
Geom File=g01
Flow File=f01
Plan File=p01
Plan File=p02
Y Axis Title=Elevation
X Axis Title(PF)=Main Channel Distance
X Axis Title(XS)=Station
BEGIN DESCRIPTION:
HCFCD MODEL SUMMARY METADATA
The purpose of this summary is to document the high points of hydrologic and hydraulic models filed within the HCFCD Model and Map Management (M3) system.  The document includes references to the project that prompted the creation or update of the model.
DESCRIPTION OF PROJECT:
The following model was the hydraulic model which represented the effective condition of Harris County's watersheds.
PURPOSE OF PROJECT:
Development of effective models to support the National Flood Insurance Program.
HCFCD Watershed Unit ID: P
M3 Study Identifier: 2007_Effective_P
Engineer: HCFCD
Project Name: EffectiveFEMA Study for watershed Greens Bayou (P)
Study Completion Date: 6/18/2007
FEMA Case Number: [No Data]
FEMA Approval Date: [No Date in Database]
Vertical Datum: NAVD 1988
Datum Note: 2001 ADJ
HYDRAULICS
HCFCD Unit No.:  P110-00-00
Hydraulic Program Name: HEC-RAS
Hydraulic Program Version: 3.0.1
Steady Hydraulic Model: Yes
Unsteady Hydraulic Model: No
Update1: The effective FEMA hydraulic model for unit number P110-00-00 has been updated by FEMA LOMR 16-06-08160P with an effective date of 1/20/2017.
END DESCRIPTION:
DSS Export Rating Curves= 0
DSS Export Rating Curve Sorted= 0
DSS Export Volume Flow Curves= 0
DXF Filename=C:\Temp\SG-LOMR\P110-00-00\5280.3.dxf
DXF OffsetX= 0
DXF OffsetY= 0
DXF ScaleX= 1
DXF ScaleY= 1

--- P110-00-00.p01 (plan) ---

Plan Title=Effective Multi-Profile 2017
Version=Version 3.0.1  May 2012
Short Identifier=Eff+LOMR MP
Geom File=g01
Flow File=f01
Subcritical Flow
K Sum by GR= 0
Std Step Tol= 0.01
Critical Tol= 0.01
Num of Std Step Trials= 20
Max Error Tol= 0.3
Flow Tol Ratio= 0.001
Split Flow NTrial= 30
Split Flow Tol= 0.02
Split Flow Ratio= 0.02
Log Output Level= 0
Friction Slope Method= 1
Unsteady Friction Slope Method= 2
Parabolic Critical Depth
Global Vel Dist= 0 , 0 , 0
Global Log Level= 0
CheckData=True
Encroach Param=-1 ,0,0, 0
BEGIN DESCRIPTION:
FEMA Effective Multi-Profile June 2007" + LOMR 16-06-0816P
END DESCRIPTION:
Computation Interval=1HOUR
Output Interval=1HOUR
Run HTab= 0
Run UNet= 0
Run PostProcess= 0
UNET Theta= 1
UNET ZTol= 0.02
UNET ZSATol= 0.1
UNET MxIter= 20
UNET MaxInSteps= 20
UNET DtIC= 0
UNET DtMin= 0
UNET MaxCRTS= 20
UNET WFStab= 2
UNET SFStab= 1
UNET WFX= 1
UNET SFX= 1
UNET Convert EG Bridges=-1
UNET Use Existing IB Tables=-1
Instantaneous Interval=1HOUR
Write IC File= 0
Write Velocity= 0
Write Detailed= 0

--- P110-00-00.p02 (plan) ---

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Plan Title=Effective Floodway 2017
Short Identifier=EFF+LOMR FW
Geom File=g01
Flow File=f02
Encroach Param=-1 ,0,0, 2
Encroach River=P110-00-00
Encroach Reach=P110-00-00_0008
Encroach Node=8636.91
       1  4978.6  5023.4
Encroach Node=7776.84
       1 4911.61 5057.58
Encroach Node=7646.68
       1 4970.54  5081.9
Encroach Node=7486.61
       1 4943.79 5028.04
Encroach Node=7469.00
       1 4943.79 5028.04
Encroach Node=7451.39
       1 4940.05 5029.18
Encroach Node=7193.52
       1  4963.7 5021.61
Encroach Node=6823.8
       1    4957    5037
Encroach Node=6119.4
       1    4980    5020
Encroach Node=5280.3
       1  4919.1  5022.8
Encroach Node=4742.0
       1    4964  5041.8
Encroach Node=3886.4
       1  4936.1  5066.1
Encroach Node=3359.7
       1    4940    5032
Encroach Node=3253.5
       1    4952    5033
Encroach Node=3242.0
       1  4965.9  5026.9
Encroach Node=3240.2
       1  4965.9  5026.9
Encroach Node=3224.2
       1  4965.9  5026.9
Encroach Node=3208.2
       1  4965.9  5026.9
Encroach Node=2814.0
       1    4971    5052
Encroach Node=2220.2
       1    4965    5050
Encroach Node=1647.0
       1    4900    5075
Encroach Node=799.5
       1    4910    5090
FEMA Effective Floodway June 2007 + LOMR 16-06-8160P

--- P110-00-00.f01 (steady flow) ---

Flow Title=Effective Multi-Profile (Jan 20,2017)
Version=Version 3.0.1  May 2012
Number of Profiles= 4
Profile Names=10PCT_10yr, 2PCT_50yr, 1PCT_100yr, 0.2PCT_500yr
River Rch & RM=P110-00-00,P110-00-00_0008 ,8636.91
     912    1314    1519    2088
River Rch & RM=P110-00-00,P110-00-00_0008 ,7776.84
     950    1369    1582    2175
River Rch & RM=P110-00-00,P110-00-00_0008 ,6823.8
     981    1414    1635    2247
River Rch & RM=P110-00-00,P110-00-00_0008 ,6119.4
    1020    1471    1700    2336
River Rch & RM=P110-00-00,P110-00-00_0008 ,5280.3
    1046    1508    1743    2396
River Rch & RM=P110-00-00,P110-00-00_0008 ,4742
    1088    1569    1813    2493
River Rch & RM=P110-00-00,P110-00-00_0008 ,3886.4
    1121    1616    1867    2567
River Rch & RM=P110-00-00,P110-00-00_0008 ,3253.5
    1176    1695    1959    2693
River Rch & RM=P110-00-00,P110-00-00_0008 ,2220.2
    1208    1741    2012    2766
River Rch & RM=P110-00-00,P110-00-00_0008 ,1647
    1256    1811    2093    2877
Boundary for River Rch & Prof#=P110-00-00,P110-00-00_0008 , 1
Up Type= 0
Dn Type= 3
Dn Slope=.00079
Boundary for River Rch & Prof#=P110-00-00,P110-00-00_0008 , 2
Up Type= 0
Dn Type= 3
Dn Slope=.00079
Boundary for River Rch & Prof#=P110-00-00,P110-00-00_0008 , 3
Up Type= 0
Dn Type= 3
Dn Slope=.00079
Boundary for River Rch & Prof#=P110-00-00,P110-00-00_0008 , 4
Up Type= 0
Dn Type= 3
Dn Slope=.00079
DSS Import GetInterval= 0
DSS Import GetPeak= 0
DSS Import FillOption= 0

--- P110-00-00.f02 (steady flow) ---

Flow Title=Effective Floodway (Jan 20,2017)
Version=Version 3.0.1  May 2012
Number of Profiles= 2
Profile Names=1PCT_100yr, 1PCTFloodway_100yr
River Rch & RM=P110-00-00,P110-00-00_0008 ,8636.91
    1519    1519
River Rch & RM=P110-00-00,P110-00-00_0008 ,7776.84
    1582    1582
River Rch & RM=P110-00-00,P110-00-00_0008 ,6823.8
    1635    1635
River Rch & RM=P110-00-00,P110-00-00_0008 ,6119.4
    1700    1700
River Rch & RM=P110-00-00,P110-00-00_0008 ,5280.3
    1743    1743
River Rch & RM=P110-00-00,P110-00-00_0008 ,4742
    1813    1813
River Rch & RM=P110-00-00,P110-00-00_0008 ,3886.4
    1867    1867
River Rch & RM=P110-00-00,P110-00-00_0008 ,3253.5
    1959    1959
River Rch & RM=P110-00-00,P110-00-00_0008 ,2220.2
    2012    2012
River Rch & RM=P110-00-00,P110-00-00_0008 ,1647
    2093    2093
Boundary for River Rch & Prof#=P110-00-00,P110-00-00_0008 , 1
Up Type= 0
Dn Type= 3
Dn Slope=.00079
Boundary for River Rch & Prof#=P110-00-00,P110-00-00_0008 , 2
Up Type= 0
Dn Type= 3
Dn Slope=.00079
DSS Import GetInterval= 0
DSS Import GetPeak= 0
DSS Import FillOption= 0

--- P110-00-00.g01 (geometry) ---

Geom Title=P110-00-00 (Jan 20, 2017)
Version=Version 3.0.1  May 2012

River Reach=P110-00-00      ,P110-00-00_0008
Reach XY= 30
      3168914.85     13868138.82       3168622.5       13867668.
        3168551.       13867448.      3168591.42     13867250.38
      3168522.75     13867211.59      3168602.93     13867087.37
      3168539.89     13866999.59        3168569.       13866625.
      3168521.75       13866435.      3168582.25       13866049.
        3168794.       13865813.        3168837.       13865676.
      3168644.25       13865303.        3168325.       13865019.
        3168569.       13864757.      3168935.25       13864760.
        3169097.       13864702.      3169168.25       13864439.
      3169045.75       13864283.      3168880.25       13864246.
      3168724.25       13863707.      3168748.75       13863574.
       3168625.5       13863407.       3168625.5       13863244.
      3168499.75       13863106.        3168502.       13862938.
        3168226.       13862709.       3168129.5       13862486.
      3167816.75       13862341.      3167805.28     13862151.66

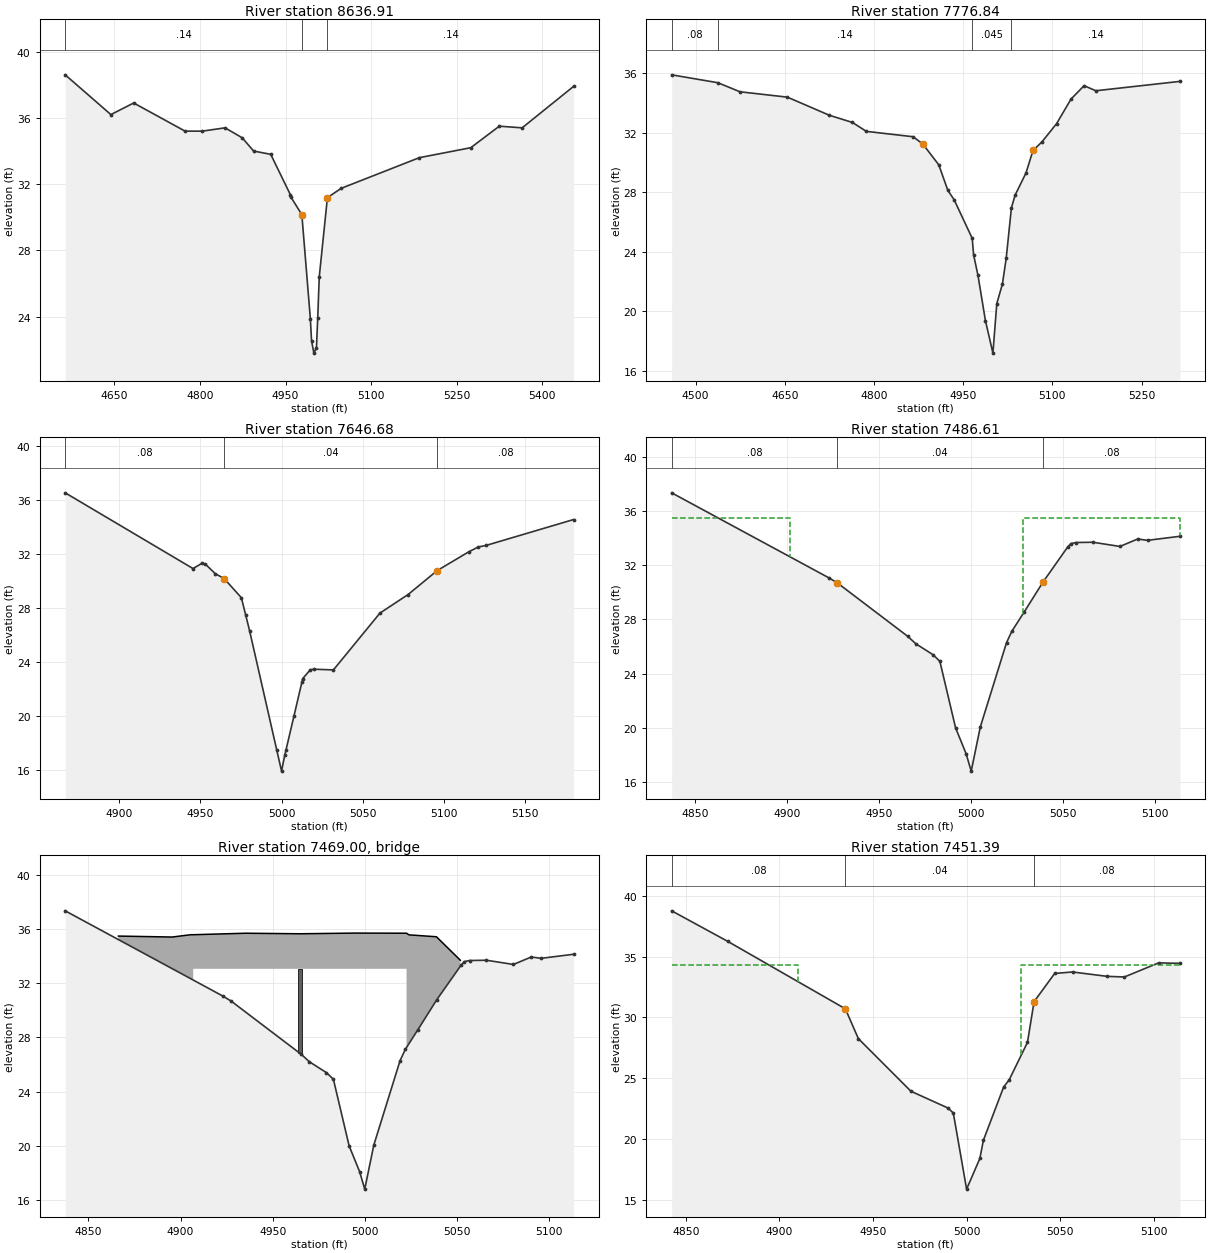
Type RM Length L Ch R = 1 ,8636.91 ,828.5,860.07,891.7
BEGIN DESCRIPTION:
Previous Cross Section 8555.0
END DESCRIPTION:
XS GIS Cut Line= 3
      3169296.34     13867927.68      3168753.57     13868228.09
      3168533.43      13868384.5
#Sta/Elev= 25
  4564.1    38.6  4644.1    36.2  4684.1    36.9  4774.1    35.2  4804.1    35.2
  4844.1    35.4  4874.1    34.8  4894.1      34  4924.1    33.8  4958.7   31.35
  4958.9   31.25  4978.6   30.16  4993.5   23.88  4995.6   22.54  4999.7    21.8
  5004.2   22.13  5006.4    23.9  5009.1    26.4  5023.4   31.19  5047.7   31.75
  5184.5    33.6  5274.5    34.2  5324.5    35.5  5364.5    35.4  5454.5    37.9
#Mann= 3 ,-1 , 0
  4564.1     .14       0  4978.6    .045       0  5023.4     .14       0
Bank Sta=4978.6,5023.4
XS Rating Curve= 0
Exp/Cntr=.3,.1

Type RM Length L Ch R = 1 ,7776.84 ,212.4,130.16,71.74
BEGIN DESCRIPTION:
Previous Section 7698.9, Revised Per CNP Survey 2012
END DESCRIPTION:
XS GIS Cut Line= 5
      3169102.39     13867443.46      3168774.66     13867401.13
      3168561.18     13867387.36      3168251.28     13867373.58
      3168251.26     13867373.58
#Sta/Elev= 30
 4459.94   35.88 4537.54   35.35 4574.85   34.74 4654.47   34.38 4725.21   33.16
 4763.81   32.68 4787.25   32.08 4865.94   31.72 4882.19   31.23 4909.02   29.83
 4924.19   28.12 4934.88   27.48 4965.23   24.89 4967.47    23.8  4974.9    22.4
 4987.38   19.37    5000   17.18 5006.53   20.51 5015.95   21.82 5022.34   23.55
 5031.12   26.95 5037.38    27.8 5055.64   29.29 5067.43    30.8 5082.36   31.37
 5107.05    32.6  5131.3   34.25 5153.26   35.15 5173.03   34.81 5314.52   35.44
#Mann= 4 ,-1 , 0
 4459.94     .08       0 4537.54     .14       0 4965.23    .045       0
 5031.12     .14       0
Bank Sta=4882.19,5067.43
XS Rating Curve= 0
Exp/Cntr=.3,.1

Type RM Length L Ch R = 1 ,7646.68 ,71.47,160.07,149.53
BEGIN DESCRIPTION:
CNP Survey 2012
END DESCRIPTION:
XS GIS Cut Line= 3
      3168708.12      13867203.6      3168528.95     13867315.28
      3168427.15     13867310.01
#Sta/Elev= 26
 4866.75   36.54 4945.45   30.93 4951.01   31.32 4952.95   31.27 4959.16   30.55
 4964.63   30.19 4975.23   28.77 4977.87    27.5 4980.29   26.33    4997    17.5
    5000   15.92 5001.98   17.11 5002.75    17.5 5007.63      20  5012.5    22.5
 5013.05   22.78  5017.7   23.43 5020.01   23.47 5031.93   23.42  5060.6   27.63
 5077.87      29 5095.86   30.78  5115.3   32.17 5121.18   32.53 5126.17   32.65
 5179.81   34.56
#Mann= 3 , 0 , 0
 4866.75     .08       0 4964.63     .04       0 5095.86     .08       0
Bank Sta=4964.63,5095.86
XS Rating Curve= 0
Exp/Cntr=.5,.3

Type RM Length L Ch R = 1 ,7486.61 ,34.17,35.22,36.1
BEGIN DESCRIPTION:
CNP Survey 2012
END DESCRIPTION:
XS GIS Cut Line= 2
      3168708.46     13867188.95      3168432.83     13867174.67
#Sta/Elev= 23
 4837.36   37.33 4922.83   31.06 4927.37   30.69 4965.53   26.76 4969.94   26.21
 4979.22   25.41 4982.98   24.92 4991.51   20.02 4997.23   18.11    5000   16.83
 5004.93   20.08 5019.19    26.3 5022.05   27.13 5028.66   28.53    5039   30.76
 5052.43   33.35 5054.15   33.59 5056.89   33.67 5066.07   33.69 5080.73   33.38
 5090.43   33.93 5095.72   33.83 5113.36   34.13
#Mann= 3 , 0 , 0
 4837.36     .08       0 4927.37     .04       0    5039     .08       0
#XS Ineff= 2 , 0
 4837.36 4901.52   35.47 5028.04 4837.36   35.47
Permanent Ineff=
       F       F
Bank Sta=4927.37,5039
XS Rating Curve= 0
Exp/Cntr=.5,.3

Type RM Length L Ch R = 3 ,7469.00 ,,,
BEGIN DESCRIPTION:
Proposed CNP Bridge
END DESCRIPTION:
Bridge Culvert--1,0,-1,-1, 0
Deck Dist Width WeirC Skew NumUp NumDn MinLoCord MaxHiCord MaxSubmerge Is_Ogee
6.17,24,2.6,0, 11, 11, , , .95, 0, 0,0,,
 4866.25 4895.48 4905.53 4906.86 4935.28 4964.78 4994.78  5022.7 5024.03 5038.93
 5051.91
   35.47    35.4   35.57   35.57   35.68   35.64   35.69   35.68   35.56   35.42
   33.69
                           33.06   33.06   33.06   33.06   33.06
        
 4871.14 4900.61 4910.66 4911.99 4940.41 4969.67 4999.91 5027.83 5029.16 5044.06
  5056.8
   35.47   35.41   35.57   35.57   35.68   35.64   35.69   35.68   35.56   35.42
   33.69
                           33.09   33.09   33.09   33.09   33.09
        
Pier Skew, UpSta & Num, DnSta & Num=  ,4964.78, 4 ,4969.67, 4 , 3 , 3 , 0 ,,
     1.5     1.5     2.5     2.5
      15   31.02   31.02    33.1
     1.5     1.5     2.5     2.5
      15   31.02   31.02    33.1
BR Coef=-1 , 0 , 0 ,1.25, 0 ,,,.8,-1,2,0,
WSPro=,,,, 1 ,,,, 0 ,,,, 0 ,,,,-1 ,-1 ,-1 , 0 , 0 , 0 , 0 , 0
BC Design=,, 0 ,, 0 ,,,,,,

Type RM Length L Ch R = 1 ,7451.39 ,216.17,257.87,214
BEGIN DESCRIPTION:
CNP Survey 2012
END DESCRIPTION:
XS GIS Cut Line= 2
      3168709.97     13867154.98      3168438.86     13867140.93
#Sta/Elev= 20
 4842.49   38.77 4872.41   36.26 4935.26   30.71 4942.18   28.26 4970.28   23.93
 4990.08   22.55 4992.91   22.14    5000   15.88 5007.07    18.4    5009   19.91
 5019.78   24.28 5022.74   24.87 5032.51   27.95 5036.04    31.3 5047.04   33.62
 5056.57   33.74  5075.1   33.38 5084.27   33.33 5102.58   34.49 5113.97   34.45
#Mann= 3 , 0 , 0
 4842.49     .08       0 4935.26     .04       0 5036.04     .08       0
#XS Ineff= 2 , 0
 4842.49 4910.16   34.29 5029.18 4842.49   34.29
Permanent Ineff=
       F       F
Bank Sta=4935.26,5036.04
XS Rating Curve= 0
Exp/Cntr=.5,.3

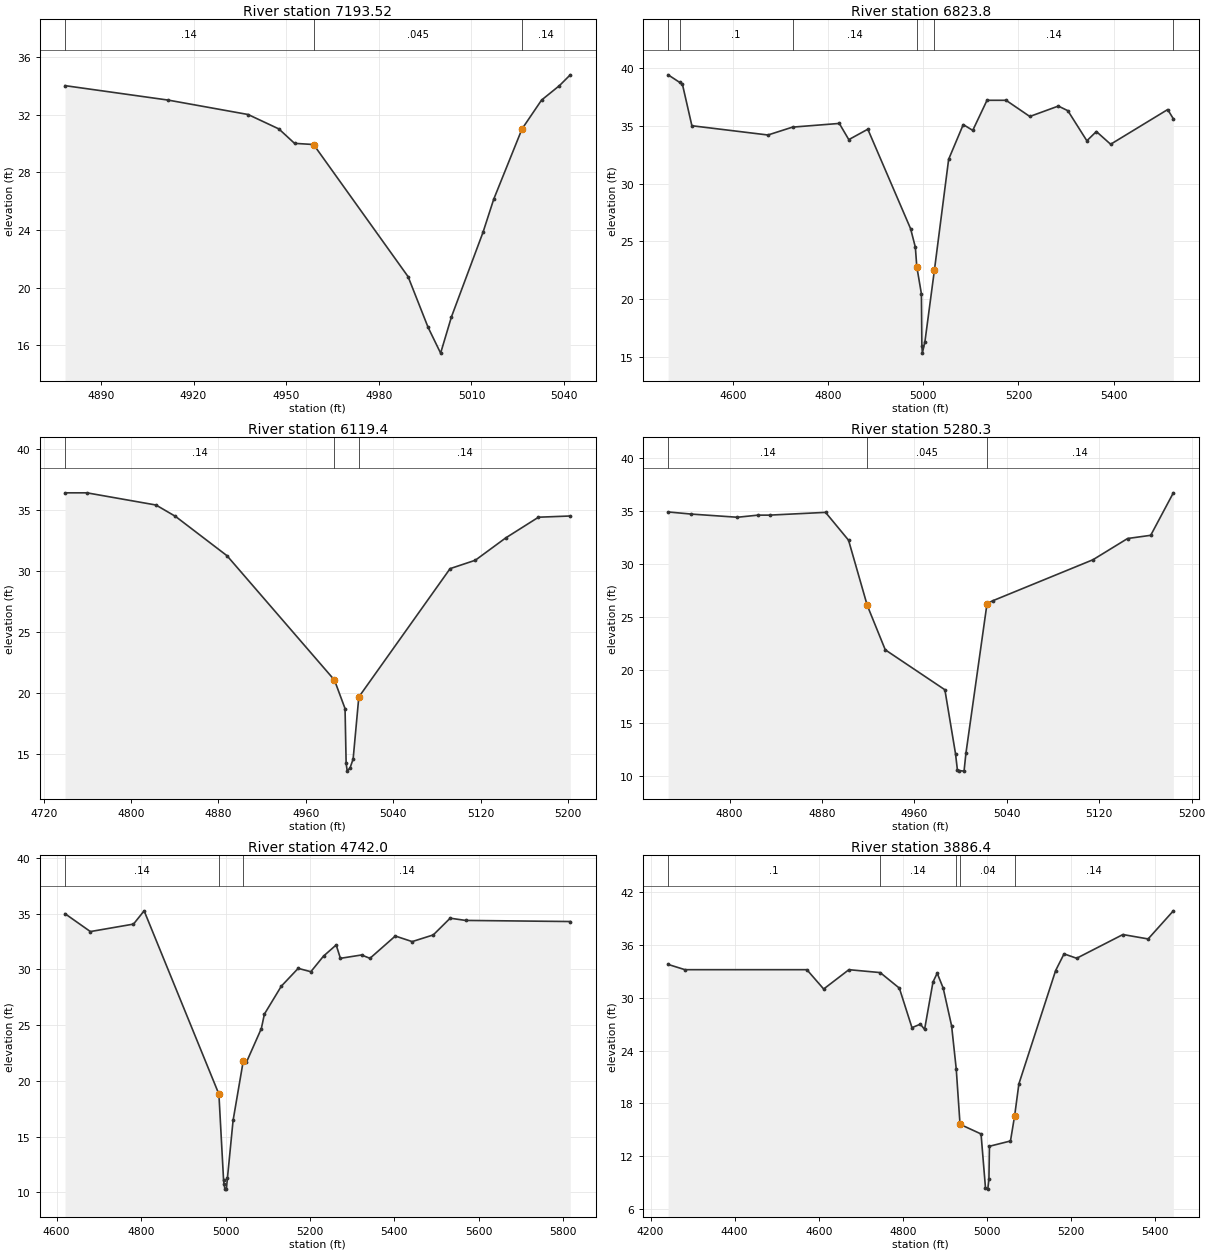
Type RM Length L Ch R = 1 ,7193.52 ,381.61,369.72,357
BEGIN DESCRIPTION:
CNP Survey 2012
END DESCRIPTION:
XS GIS Cut Line= 2
      3168658.08     13866939.16       3168494.7      13866930.7
#Sta/Elev= 16
 4878.39      34 4911.74      33 4937.65      32 4947.63      31  4952.7      30
 4958.86   29.92 4989.47   20.76 4995.94   17.25    5000   15.46 5003.52   17.98
 5013.72   23.83  5017.2   26.13 5026.36      31 5032.69      33 5038.47      34
 5041.99   34.75
#Mann= 3 , 0 , 0
 4878.39     .14       0 4958.86    .045       0 5026.36     .14       0
Bank Sta=4958.86,5026.36
XS Rating Curve= 0
Exp/Cntr=.3,.1

Type RM Length L Ch R = 1 ,6823.8  ,679,704.4,825.2
BEGIN DESCRIPTION:
Cross Section 6823.8-Interpolated
END DESCRIPTION:
XS GIS Cut Line= 4
      3169089.14     13866565.15      3168629.44     13866549.48
      3168483.17     13866586.05      3168039.14     13866669.63
#Sta/Elev= 30
  4463.1    39.4  4487.3   38.75  4493.1    38.6  4513.1      35  4673.1    34.2
  4724.7   34.88  4823.1    35.2  4843.1    33.8  4883.1    34.7  4973.1    26.1
  4983.1    24.5  4986.1   22.82  4995.8   20.48  4996.8   15.99  4997.8   15.35
  5003.2   16.34  5023.1    22.5  5053.1    32.1  5083.8    35.1  5103.8    34.6
  5133.8    37.2  5173.8    37.2  5223.8    35.8  5283.8    36.7  5303.8    36.3
  5343.8    33.7  5363.8    34.5  5393.8    33.4  5513.8    36.4  5525.7    35.6
#Mann= 7 , 1 , 0
  4463.1      .2       0  4463.1     .08       0  4487.3      .1       0
  4724.7     .14       0  4986.1    .045       0  5023.1     .14       0
  5525.7      .2       0
Bank Sta=4986.1,5023.1
XS Rating Curve= 0
Exp/Cntr=.3,.1

Type RM Length L Ch R = 1 ,6119.4  ,903.3,839.1,712.1
BEGIN DESCRIPTION:
Cross Section 6119.4
END DESCRIPTION:
XS GIS Cut Line= 3
      3168921.72     13866065.78      3168850.41     13866022.74
       3168538.4     13865807.56
#Sta/Elev= 17
  4739.6    36.4  4759.6    36.4  4822.8    35.4  4840.6   34.47  4887.8   31.24
  4986.1   21.04  4995.8    18.7  4996.8   14.21  4997.8   13.57  5000.4   13.84
  5003.2   14.56  5008.4   19.65  5091.9   30.18    5115   30.87  5142.8    32.7
  5172.8    34.4  5201.9    34.5
#Mann= 3 , 1 , 0
  4739.6     .14       0  4986.1    .045       0  5008.4     .14       0
Bank Sta=4986.1,5008.4
XS Rating Curve= 0
Exp/Cntr=.3,.1

Type RM Length L Ch R = 1 ,5280.3  ,285.2,538.3,652.6
BEGIN DESCRIPTION:
Cross Section 5280.3
END DESCRIPTION:
XS GIS Cut Line= 3
      3168755.45     13865128.29      3168678.25     13865118.88
      3168398.48     13865344.85
#Sta/Elev= 21
  4746.7    34.9  4766.7    34.7  4806.7    34.4  4824.5    34.6  4834.5    34.6
    4883   34.86  4902.9   32.24  4919.1    26.1  4934.7   21.92  4986.3   18.16
  4995.5   12.15  4997.1   10.65  4998.8   10.55  5002.9    10.5  5004.5   12.16
  5022.8   26.28    5028   26.55  5114.5    30.4  5144.5    32.4  5164.5    32.7
  5184.1    36.7
#Mann= 3 , 1 , 0
  4746.7     .14       0  4919.1    .045       0  5022.8     .14       0
Bank Sta=4919.1,5022.8
XS Rating Curve= 0
Exp/Cntr=.3,.1

Type RM Length L Ch R = 1 ,4742.0  ,829.1,855.6,756.4
BEGIN DESCRIPTION:
Cross Section 4742.0
END DESCRIPTION:
XS GIS Cut Line= 5
      3168793.49     13865021.29      3168732.05     13865000.52
       3168377.8     13864799.61      3167926.87     13864645.73
      3167683.91     13864595.75
#Sta/Elev= 29
  4619.9      35  4679.9    33.4    4782   34.07  4807.2   35.26  4984.3   18.82
  4995.4   11.09  4996.5   10.74  4998.6    10.3    5002   10.32  5004.6   11.32
  5017.9   16.46  5041.8   21.75  5049.6   21.69  5084.8    24.7  5092.1      26
  5132.1    28.5  5172.1    30.1  5202.1    29.8  5232.1    31.2  5262.1    32.2
  5272.1      31  5322.1    31.3  5342.1      31  5402.1      33  5442.1    32.5
  5492.1    33.1  5532.1    34.6  5568.5    34.4  5816.6    34.3
#Mann= 3 , 1 , 0
  4619.9     .14       0  4984.3    .045       0  5041.8     .14       0
Bank Sta=4984.3,5041.8
XS Rating Curve= 0
Exp/Cntr=.3,.1

Type RM Length L Ch R = 1 ,3886.4  ,503.1,526.7,549.1
BEGIN DESCRIPTION:
Cross Section 3886.4-Interpolated
END DESCRIPTION:
XS GIS Cut Line= 4
       3169905.9     13864546.77      3169261.53     13864543.51
      3168984.66     13864559.18      3168711.08     13864499.52
#Sta/Elev= 30
  4241.8    33.8  4281.8    33.2  4571.8    33.2  4611.8      31  4671.8    33.2
  4746.2   32.87  4791.8    31.1  4821.8    26.6  4841.8      27  4851.8    26.4
  4871.8    31.8  4881.8    32.8  4896.1    31.1  4916.1    26.8  4927.1    21.9
  4936.1    15.6  4986.1    14.5 4996.64    8.36 5002.14    8.22 5004.84    9.36
  5006.1    13.1  5056.1    13.7  5066.1    16.6  5076.1    20.2  5163.5    33.1
  5183.5      35  5213.5    34.5  5323.5    37.2  5383.5    36.7  5443.5    39.9
#Mann= 5 , 1 , 0
  4241.8      .1       0  4746.2     .14       0  4927.1     .14       0
  4936.1     .04       0  5066.1     .14       0
Bank Sta=4936.1,5066.1
XS Rating Curve= 0
Exp/Cntr=.3,.1

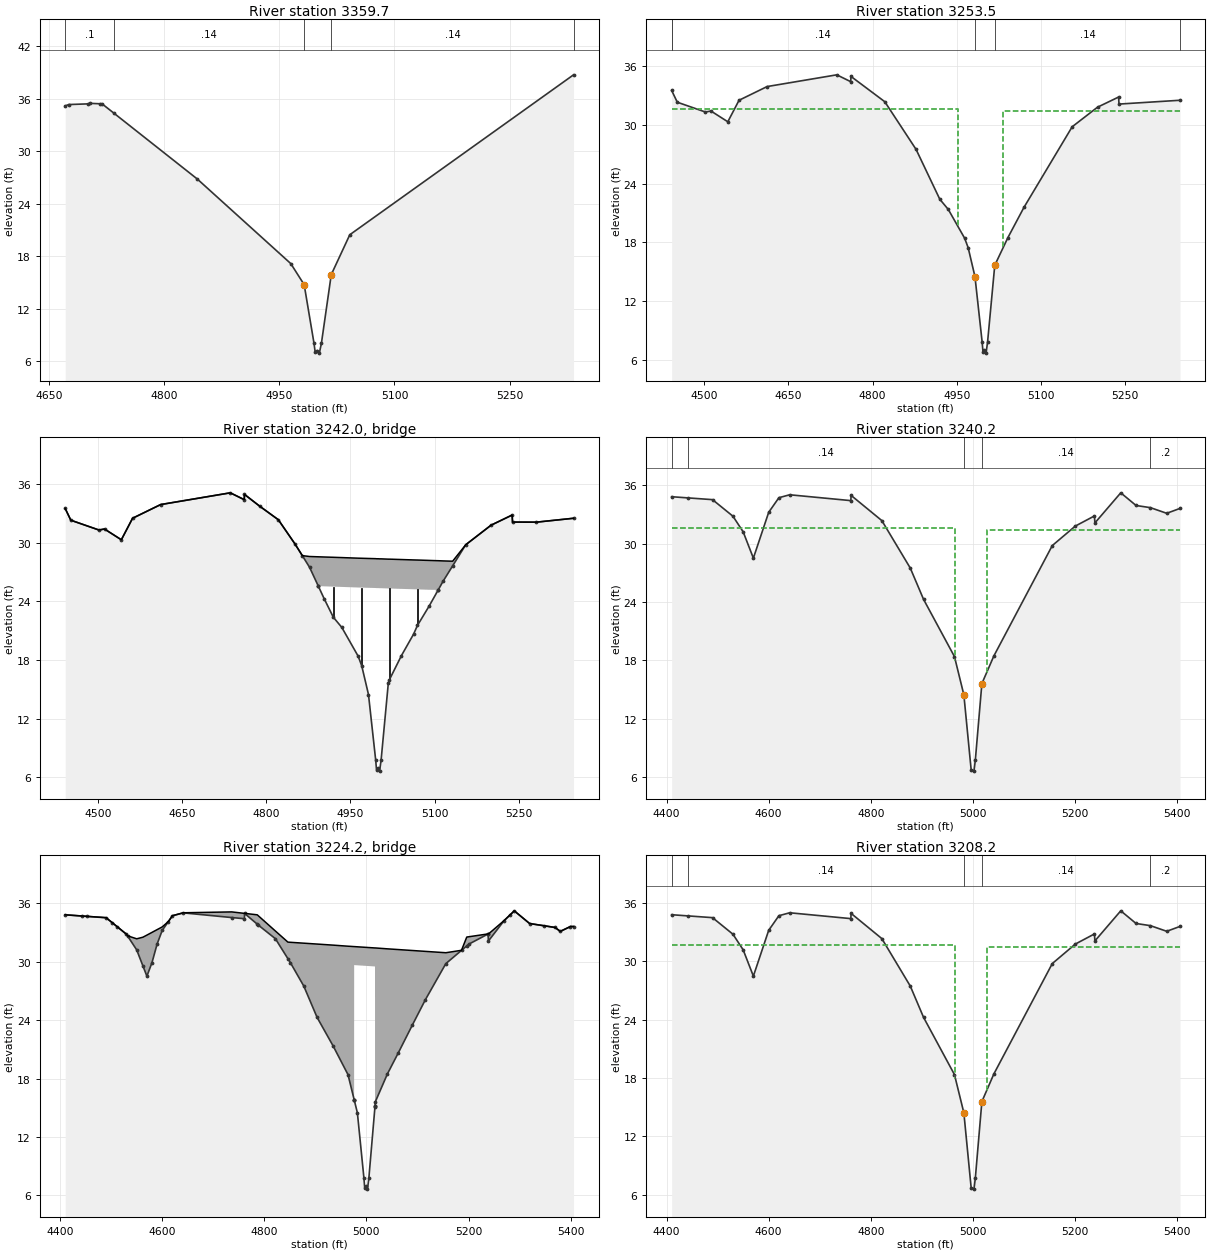
Type RM Length L Ch R = 1 ,3359.7  ,104.1,106.2,111.3
BEGIN DESCRIPTION:
Cross Section 3359.7-Interpolated
END DESCRIPTION:
XS GIS Cut Line= 6
      3169192.56     13864167.43      3169144.91     13864162.38
      3169021.78     13864178.17      3168904.96      13864212.9
      3168832.34     13864238.15       3168554.5     13864326.56
#Sta/Elev= 18
    4671    35.2  4675.5   35.36  4701.2   35.44  4702.8    35.5  4716.3   35.45
  4718.9   35.45  4734.1    34.4    4843   26.85  4964.9   17.17 4982.34   14.76
 4995.14    8.07 4996.64    7.07 4999.14    7.23 5002.14    6.93 5004.84    8.07
 5017.64   15.91  5041.8   20.47  5333.3   38.76
#Mann= 5 , 1 , 0
    4671      .1       0  4734.1     .14       0 4982.34     .04       0
 5017.64     .14       0  5333.3      .2       0
Bank Sta=4982.34,5017.64
XS Rating Curve= 0
Exp/Cntr=.5,.3

Type RM Length L Ch R = 1 ,3253.5  ,13.3,13.3,13.3
BEGIN DESCRIPTION:
Upstream Section of Bridge/Culvert/Weir
END DESCRIPTION:
XS GIS Cut Line= 2
      3169389.79     13864141.06      3168485.55      13864093.3
#Sta/Elev= 30
  4442.1   33.52  4452.1   32.32  4502.1   31.32  4512.1   31.42  4542.1   30.32
  4562.1   32.52  4612.1   33.92  4736.2   35.12 4761.04   34.42 4761.44   34.96
 4821.74   32.37 4877.44    27.5 4919.74    22.4 4934.84   21.36 4963.94   18.42
 4970.24   17.45 4982.34    14.5 4995.14    7.81 4996.64    6.81 4999.14    6.97
 5002.14    6.67 5004.84    7.81 5017.64   15.65 5041.14   18.49 5069.64   21.57
 5155.54   29.81 5200.64   31.81 5238.24   32.85 5238.94   32.13  5347.6   32.52
#Mann= 5 , 1 , 0
  4442.1      .2       0  4442.1     .14       0 4982.34    .045       0
 5017.64     .14       0  5347.6      .2       0
#XS Ineff= 2 , 0
       0    4952    31.6    5033       0    31.4
Permanent Ineff=
       F       F
Bank Sta=4982.34,5017.64
XS Rating Curve= 0
Exp/Cntr=.5,.3

Type RM Length L Ch R = 3 ,3242.0  ,,,
BEGIN DESCRIPTION:
36" DIAMETER PIPELINE U/S OF ACCESS ROAD
END DESCRIPTION:
Bridge Culvert--1,0,-1,-1, 0
Deck Dist Width WeirC Skew NumUp NumDn MinLoCord MaxHiCord MaxSubmerge Is_Ogee
10,3,2.6,0, 44, 44, , , .95, 0, 1,1,,
  4442.1  4452.1  4502.1  4512.1  4542.1  4562.1  4612.1  4736.2 4761.04 4761.44
 4788.64 4821.74 4851.34 4864.54 4877.44 4893.15 4893.24 4903.44 4919.74 4934.84
 4963.94 4970.24 4982.34 4995.14 4996.64 4999.14 5002.14 5004.84 5017.64 5019.74
 5041.14 5062.64 5069.64 5090.04 5106.63 5106.74 5115.44 5132.24 5155.54 5200.64
 5238.24 5238.94  5281.3  5347.6
    33.5    32.3    31.3    31.4    30.3    32.5    33.9    35.1    34.4   34.94
   33.73   32.35   29.88   28.68   28.59   28.56   28.56   28.54   28.51   28.48
   28.42   28.41   28.39   28.37   28.36   28.36   28.35   28.35   28.32   28.32
   28.28   28.24   28.23   28.19   28.16   28.16   28.14   28.11   29.79   31.79
   32.83   32.11    32.1    32.5
    33.5    32.3    31.3    31.4    30.3    32.5    33.9    35.1    34.4   34.94
   33.73   32.35   29.88   28.67   27.48   25.54   25.56   25.54   25.51   25.48
   25.42   25.41   25.39   25.37   25.36   25.36   25.35   25.35   25.32   25.32
   25.28   25.24   25.23   25.19   25.18   25.19   26.08   27.63   29.79   31.79
   32.83   32.11    32.1    32.5
  4442.1  4452.1  4502.1  4512.1  4542.1  4562.1  4612.1  4736.2 4761.04 4761.44
 4788.64 4821.74 4851.34 4864.54 4877.44 4893.15 4893.24 4903.44 4919.74 4934.84
 4963.94 4970.24 4982.34 4995.14 4996.64 4999.14 5002.14 5004.84 5017.64 5019.74
 5041.14 5062.64 5069.64 5090.04 5106.63 5106.74 5115.44 5132.24 5155.54 5200.64
 5238.24 5238.94  5281.3  5347.6
    33.5    32.3    31.3    31.4    30.3    32.5    33.9    35.1    34.4   34.94
   33.73   32.35   29.88   28.68   28.59   28.56   28.56   28.54   28.51   28.48
   28.42   28.41   28.39   28.37   28.36   28.36   28.35   28.35   28.32   28.32
   28.28   28.24   28.23   28.19   28.16   28.16   28.14   28.11   29.79   31.79
   32.83   32.11    32.1    32.5
    33.5    32.3    31.3    31.4    30.3    32.5    33.9    35.1    34.4   34.94
   33.73   32.35   29.88   28.67   27.48   25.54   25.56   25.54   25.51   25.48
   25.42   25.41   25.39   25.37   25.36   25.36   25.35   25.35   25.32   25.32
   25.28   25.24   25.23   25.19   25.18   25.19   26.08   27.63   29.79   31.79
   32.83   32.11    32.1    32.5
Pier Skew, UpSta & Num, DnSta & Num=  ,4919.7, 2 ,4919.7, 2 , 0 , 0 , 0 ,,
       2       2
   21.31   26.51
       2       2
   21.31   26.51
Pier Skew, UpSta & Num, DnSta & Num=  ,4970.2, 2 ,4970.2, 2 , 0 , 0 , 0 ,,
       2       2
   16.19   26.41
       2       2
   16.19   26.41
Pier Skew, UpSta & Num, DnSta & Num=  ,5019.7, 2 ,5019.7, 2 , 0 , 0 , 0 ,,
       2       2
   14.83   26.32
       2       2
   14.83   26.32
Pier Skew, UpSta & Num, DnSta & Num=  ,5069.6, 2 ,5069.6, 2 , 0 , 0 , 0 ,,
       2       2
   20.42   26.23
       2       2
   20.42   26.23
BR Coef= 1 , 1 , 0 ,1.25, 0 ,,,.8,0,2,0,
WSPro=,,,, 1 ,,,, 0 ,,,, 0 ,,,,-1 ,-1 ,-1 , 0 , 0 , 0 , 0 , 0
BR U #Sta/Elev= 44
  4442.1    33.5  4452.1    32.3  4502.1    31.3  4512.1    31.4  4542.1    30.3
  4562.1    32.5  4612.1    33.9  4736.2    35.1 4761.04    34.4 4761.44   34.94
 4788.64   33.73 4821.74   32.35 4851.34   29.88 4864.54   28.67 4877.44   27.48
 4893.15   25.54 4893.24   25.53 4903.44   24.27 4919.74   22.38 4934.84   21.34
 4963.94    18.4 4970.24   17.43 4982.34   14.48 4995.14    7.79 4996.64    6.79
 4999.14    6.95 5002.14    6.65 5004.84    7.79 5017.64   15.63 5019.74   16.01
 5041.14   18.47 5062.64   20.65 5069.64   21.55 5090.04   23.49 5106.63   25.18
 5106.74   25.19 5115.44   26.08 5132.24   27.63 5155.54   29.79 5200.64   31.79
 5238.24   32.83 5238.94   32.11  5281.3    32.1  5347.6    32.5
BR U #Mann= 5
  4442.1      .2  4442.1     .14 4982.34    .045 5017.64     .14  5347.6      .2
BR U Banks=4982.34,5017.64
BR D #Sta/Elev= 44
  4442.1    33.5  4452.1    32.3  4502.1    31.3  4512.1    31.4  4542.1    30.3
  4562.1    32.5  4612.1    33.9  4736.2    35.1 4761.04    34.4 4761.44   34.94
 4788.64   33.73 4821.74   32.35 4851.34   29.88 4864.54   28.67 4877.44   27.48
 4893.15   25.54 4893.24   25.53 4903.44   24.27 4919.74   22.38 4934.84   21.34
 4963.94    18.4 4970.24   17.43 4982.34   14.48 4995.14    7.79 4996.64    6.79
 4999.14    6.95 5002.14    6.65 5004.84    7.79 5017.64   15.63 5019.74   16.01
 5041.14   18.47 5062.64   20.65 5069.64   21.55 5090.04   23.49 5106.63   25.18
 5106.74   25.19 5115.44   26.08 5132.24   27.63 5155.54   29.79 5200.64   31.79
 5238.24   32.83 5238.94   32.11  5281.3    32.1  5347.6    32.5
BR D #Mann= 5
  4442.1      .2  4442.1     .14 4982.34    .045 5017.64     .14  5347.6      .2
BR D Banks=4982.34,5017.64
BC Design=,, 0 ,, 0 ,,,,,,

Type RM Length L Ch R = 1 ,3240.2  ,32,32,32
BEGIN DESCRIPTION:
Upstream Section of Bridge/Culvert/Weir
END DESCRIPTION:
XS GIS Cut Line= 4
      3169421.27     13864137.26      3169095.76     13864118.88
      3168550.93       13864100.      3168427.12     13864088.78
#Sta/Elev= 30
  4410.1    34.8  4442.1   34.68  4490.1    34.5  4530.1    32.8  4550.1    31.2
  4570.1    28.5  4600.1    33.2  4620.1    34.7  4641.3      35    4761    34.4
  4761.4   34.94  4821.7   32.35  4877.4   27.48  4903.4   24.27  4963.9    18.4
  4982.3   14.48  4996.6    6.79  5002.1    6.65  5004.8    7.79  5017.6   15.63
  5041.1   18.47  5155.5   29.79  5200.6   31.79  5238.1   32.83  5238.9   32.11
  5289.6    35.2  5319.6    33.9  5347.6   33.68  5379.6    33.1  5405.6    33.6
#Mann= 5 , 1 , 0
  4410.1      .2       0  4442.1     .14       0  4982.3    .045       0
  5017.6     .14       0  5347.6      .2       0
#XS Ineff= 2 , 0
       0  4965.9    31.6  5026.9       0    31.4
Permanent Ineff=
       F       F
Bank Sta=4982.3,5017.6
XS Rating Curve= 0
Exp/Cntr=.5,.3

Type RM Length L Ch R = 3 ,3224.2  ,,,
BEGIN DESCRIPTION:
ACCESS ROAD
Structure ID: P10-1
END DESCRIPTION:
Bridge Culvert--1,0,-1,-1, 0
Deck Dist Width WeirC Skew NumUp NumDn MinLoCord MaxHiCord MaxSubmerge Is_Ogee
10,12,2.6,0, 45, 45, , , .95, 0, 1,1,,
  4410.1  4490.1  4530.1  4532.1  4550.1  4562.1  4570.1  4580.1  4590.1  4600.1
  4612.1  4620.1  4641.3  4736.2    4761  4761.4  4786.2  4821.7  4846.2  4851.2
  4877.4  4903.4  4934.8  4963.9 4975.91    4976 5016.79  5016.9  5017.6  5041.1
  5115.4  5155.5  5186.2  5196.5  5200.6  5238.1  5238.2  5238.9  5269.6  5289.6
  5319.6  5369.6  5379.6  5399.6  5405.6
    34.8   34.51   32.81   32.65   32.34    32.5   32.72      33   33.28   33.56
   34.11   34.71   35.01    35.1   34.95   34.95    34.8   33.14      32   31.98
   31.89    31.8   31.69   31.58   31.54   31.54    31.4    31.4    31.4   31.31
   31.05   30.91   31.16   32.52   32.55   32.84   32.84   32.83   34.21   35.21
   33.91    33.5    33.1    33.6    33.6
    34.8    34.5    32.8   32.64    31.2   29.58    28.5    29.9    31.8    33.2
    34.1    34.7      35   34.52    34.4   34.94   33.84   32.35    30.3   29.88
   27.48   24.27   21.34    18.4   15.84   29.64    29.5    15.2   15.63   18.47
   26.08   29.79   31.15   31.61   31.79   32.83   32.83   32.11    34.2    35.2
    33.9    33.5    33.1    33.6    33.6
  4410.1  4490.1  4530.1  4532.1  4550.1  4562.1  4570.1  4580.1  4590.1  4600.1
  4612.1  4620.1  4641.3  4736.2    4761  4761.4  4786.2  4821.7  4846.2  4851.2
  4877.4  4903.4  4934.8  4963.9 4975.91    4976 5016.79  5016.9  5017.6  5041.1
  5115.4  5155.5  5186.2  5196.5  5200.6  5238.1  5238.2  5238.9  5269.6  5289.6
  5319.6  5369.6  5379.6  5399.6  5405.6
    34.8   34.51   32.81   32.65   32.34    32.5   32.72      33   33.28   33.56
   34.11   34.71   35.01    35.1   34.95   34.95    34.8   33.14      32   31.98
   31.89    31.8   31.69   31.58   31.54   31.54    31.4    31.4    31.4   31.31
   31.05   30.91   31.16   32.52   32.55   32.84   32.84   32.83   34.21   35.21
   33.91    33.5    33.1    33.6    33.6
   34.75   34.45   32.75   32.59   31.15   29.53   28.45   29.85   31.75   33.15
   34.05   34.65   34.95   34.47   34.35   34.89   33.79    32.3   30.25   29.83
   27.43   24.22   21.29   18.35   15.79   29.59   29.45   15.15   15.58   18.42
   26.03   29.74    31.1   31.56   31.74   32.78   32.78   32.06   34.15   35.15
   33.85   33.45   33.05   33.55   33.55
BR Coef= 1 , 1 , 0 ,1.25, 0 ,,,.8,0,2,0,
WSPro=,,,, 1 ,,,, 0 ,,,, 0 ,,,,-1 ,-1 ,-1 , 0 , 0 , 0 , 0 , 0
BR U #Sta/Elev= 62
  4410.1    34.8  4442.1   34.68  4452.1   34.64  4490.1    34.5  4502.1   33.99
  4512.1   33.57  4530.1    32.8  4532.1   32.64  4550.1    31.2  4562.1   29.58
  4570.1    28.5  4580.1    29.9  4590.1    31.8  4600.1    33.2  4612.1    34.1
  4620.1    34.7  4641.3      35  4736.2   34.52    4761    34.4  4761.4   34.94
  4786.2   33.84  4788.6   33.73  4821.7   32.35  4846.2    30.3  4851.2   29.88
  4877.4   27.48  4903.4   24.27  4934.8   21.34  4963.9    18.4 4975.91   15.84
    4976   15.82  4976.1    15.8  4982.3   14.48  4995.1    7.79  4996.6    6.79
  4999.1    6.95  5002.1    6.65  5004.8    7.79  5016.7   15.08 5016.79   15.13
  5016.9    15.2  5017.6   15.63  5041.1   18.47  5062.6   20.65    5090   23.49
  5115.4   26.08  5155.5   29.79  5186.2   31.15  5196.5   31.61  5200.6   31.79
  5238.1   32.83  5238.2   32.83  5238.9   32.11  5269.6    34.2  5281.3   34.78
  5289.6    35.2  5319.6    33.9  5347.6   33.68  5369.6    33.5  5379.6    33.1
  5399.6    33.6  5405.6    33.6
BR U #Mann= 5
  4410.1      .2  4442.1     .14  4982.3    .045  5017.6     .14  5347.6      .2
BR U Banks=4982.3,5017.6
BR D #Sta/Elev= 62
  4410.1   34.75  4442.1   34.63  4452.1   34.59  4490.1   34.45  4502.1   33.94
  4512.1   33.52  4530.1   32.75  4532.1   32.59  4550.1   31.15  4562.1   29.53
  4570.1   28.45  4580.1   29.85  4590.1   31.75  4600.1   33.15  4612.1   34.05
  4620.1   34.65  4641.3   34.95  4736.2   34.47    4761   34.35  4761.4   34.89
  4786.2   33.79  4788.6   33.68  4821.7    32.3  4846.2   30.25  4851.2   29.83
  4877.4   27.43  4903.4   24.22  4934.8   21.29  4963.9   18.35 4975.91   15.79
    4976   15.77  4976.1   15.75  4982.3   14.43  4995.1    7.74  4996.6    6.74
  4999.1     6.9  5002.1     6.6  5004.8    7.74  5016.7   15.03 5016.79   15.08
  5016.9   15.15  5017.6   15.58  5041.1   18.42  5062.6    20.6    5090   23.44
  5115.4   26.03  5155.5   29.74  5186.2    31.1  5196.5   31.56  5200.6   31.74
  5238.1   32.78  5238.2   32.78  5238.9   32.06  5269.6   34.15  5281.3   34.73
  5289.6   35.15  5319.6   33.85  5347.6   33.63  5369.6   33.45  5379.6   33.05
  5399.6   33.55  5405.6   33.55
BR D #Mann= 5
  4410.1      .2  4442.1     .14  4982.3    .045  5017.6     .14  5347.6      .2
BR D Banks=4982.3,5017.6
BC Design=,, 0 ,, 0 ,,,,,,

Type RM Length L Ch R = 1 ,3208.2  ,394.2,394.2,394.2
BEGIN DESCRIPTION:
Downstream Section of Bridge/Culvert/Weir
END DESCRIPTION:
XS GIS Cut Line= 4
      3169411.33     13864106.84      3169085.82     13864088.46
      3168540.99     13864069.58      3168417.18     13864058.37
#Sta/Elev= 30
  4410.1   34.75  4442.1   34.63  4490.1   34.45  4530.1   32.75  4550.1   31.15
  4570.1   28.45  4600.1   33.15  4620.1   34.65  4641.3   34.95    4761   34.35
  4761.4   34.89  4821.7    32.3  4877.4   27.43  4903.4   24.22  4963.9   18.35
  4982.3   14.43  4996.6    6.74  5002.1     6.6  5004.8    7.74  5017.6   15.58
  5041.1   18.42  5155.5   29.74  5200.6   31.74  5238.1   32.78  5238.9   32.06
  5289.6   35.15  5319.6   33.85  5347.6   33.63  5379.6   33.05  5405.6   33.55
#Mann= 5 , 1 , 0
  4410.1      .2       0  4442.1     .14       0  4982.3    .045       0
  5017.6     .14       0  5347.6      .2       0
#XS Ineff= 2 , 0
       0  4965.9    31.6  5026.9       0    31.4
Permanent Ineff=
       F       F
Bank Sta=4982.3,5017.6
XS Rating Curve= 0
Exp/Cntr=.5,.3

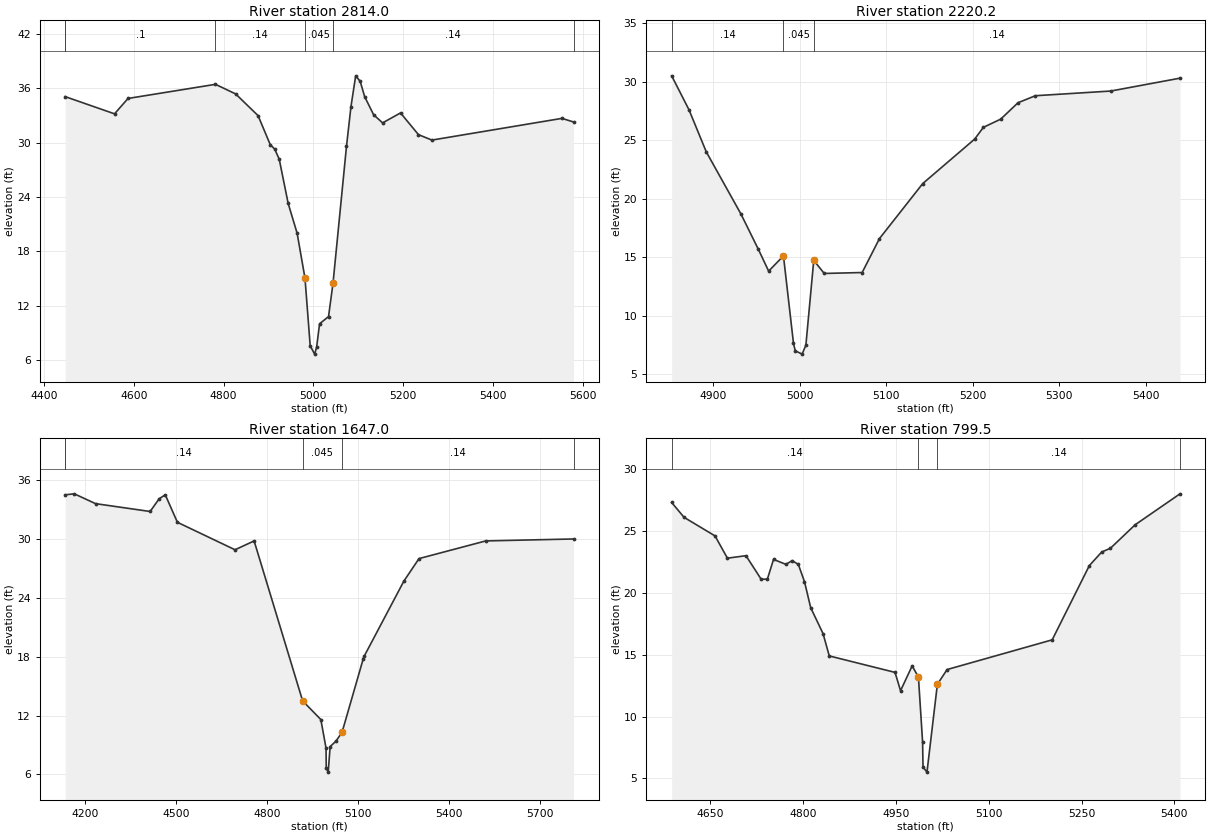
Type RM Length L Ch R = 1 ,2814.0  ,589.2,593.8,582.8
BEGIN DESCRIPTION:
Cross Section 2814.0-Interpolated
END DESCRIPTION:
XS GIS Cut Line= 4
      3169270.14     13863614.64      3168818.56     13863685.32
        3168634.     13863732.44      3168162.79     13863850.24
#Sta/Elev= 30
  4446.7    35.1  4556.7    33.2  4586.7    34.9  4781.7   36.46  4826.7    35.4
  4876.7      33  4903.8    29.8  4913.8    29.3  4923.8    28.2  4943.8    23.3
  4963.8      20  4981.3   15.04  4992.9    7.57  5002.8    6.65  5007.2    7.41
  5013.8      10  5033.8    10.8  5043.8    14.5  5073.8    29.6  5083.8      34
  5094.3    37.4  5104.3    36.8  5114.3    35.1  5134.3    33.1  5154.3    32.2
  5194.3    33.3  5234.3    30.9  5264.3    30.3  5554.3    32.7    5580    32.3
#Mann= 6 , 1 , 0
  4446.7      .2       0  4446.7      .1       0  4781.7     .14       0
  4981.3    .045       0  5043.8     .14       0    5580      .2       0
Bank Sta=4981.3,5043.8
XS Rating Curve= 0
Exp/Cntr=.3,.1

Type RM Length L Ch R = 1 ,2220.2  ,552.8,573.2,537.3
BEGIN DESCRIPTION:
Cross Section 2220.2
END DESCRIPTION:
XS GIS Cut Line= 4
      3168710.62     13863138.99      3168710.53       13863139.
      3168226.32     13863289.64      3168157.44     13863330.16
#Sta/Elev= 23
  4852.2    30.5  4872.2    27.6  4892.2      24  4932.2    18.7  4952.2    15.7
  4964.2   13.82  4981.3   15.12  4992.9    7.65  4994.9    7.02  5002.8    6.73
  5007.2    7.49  5016.3   14.74  5028.4   13.62  5072.2    13.7  5092.2    16.6
  5142.2    21.3  5202.2    25.1  5212.2    26.1  5232.2    26.8  5252.2    28.2
  5272.2    28.8  5359.3    29.2  5439.3    30.3
#Mann= 3 , 1 , 0
  4852.2     .14       0  4981.3    .045       0  5016.3     .14       0
Bank Sta=4981.3,5016.3
XS Rating Curve= 0
Exp/Cntr=.3,.1

Type RM Length L Ch R = 1 ,1647.0  ,854.8,847.5,822.9
BEGIN DESCRIPTION:
Cross Section 1647.0-Interpolated
END DESCRIPTION:
XS GIS Cut Line= 4
      3169099.59     13862662.91      3168477.94     13862621.12
      3168169.73     13862814.41      3167621.23     13863232.32
#Sta/Elev= 23
  4133.1    34.5  4163.1    34.6  4233.1    33.6  4413.1    32.8  4443.1    34.1
  4463.1    34.5  4503.1    31.7  4693.1    28.9  4756.1    29.8  4916.1    13.5
  4976.1    11.6  4993.3    8.69    4994    6.65  5000.4    6.24  5006.8    8.84
  5026.1     9.4  5046.1    10.3  5116.1    17.8  5119.9    18.1  5249.9    25.7
  5299.9      28  5519.9    29.8  5809.5      30
#Mann= 5 , 1 , 0
  4133.1      .2       0  4133.1     .14       0  4916.1    .045       0
  5046.1     .14       0  5809.5      .2       0
Bank Sta=4916.1,5046.1
XS Rating Curve= 0
Exp/Cntr=.3,.1

Type RM Length L Ch R = 1 ,799.5   ,0,0,0
BEGIN DESCRIPTION:
Cross Section 799.5
END DESCRIPTION:
XS GIS Cut Line= 4
      3168215.92      13862141.4      3168091.84     13862130.43
      3167509.51     13862173.57      3167416.39     13862236.52
#Sta/Elev= 30
  4588.1    27.3  4608.1    26.1  4658.1    24.6  4678.1    22.8  4708.1      23
  4732.6    21.1  4742.6    21.1  4752.6    22.7  4772.6    22.3  4782.6    22.6
  4792.6    22.3  4802.6    20.9  4812.6    18.8  4832.6    16.7  4842.6    14.9
  4948.8   13.57  4957.7   12.09  4976.5    14.1  4986.6   13.18  4993.3    7.96
    4994    5.92  5000.4    5.51  5017.2   12.61  5032.9    13.8  5202.6    16.2
  5262.6    22.2  5282.6    23.3  5296.6    23.6  5336.6    25.5    5409      28
#Mann= 4 , 1 , 0
  4588.1     .14       0  4986.6    .045       0  5017.2     .14       0
    5409      .2       0
Bank Sta=4986.6,5017.2
XS Rating Curve= 0
Exp/Cntr=.3,.1

Chan Stop Cuts=-1